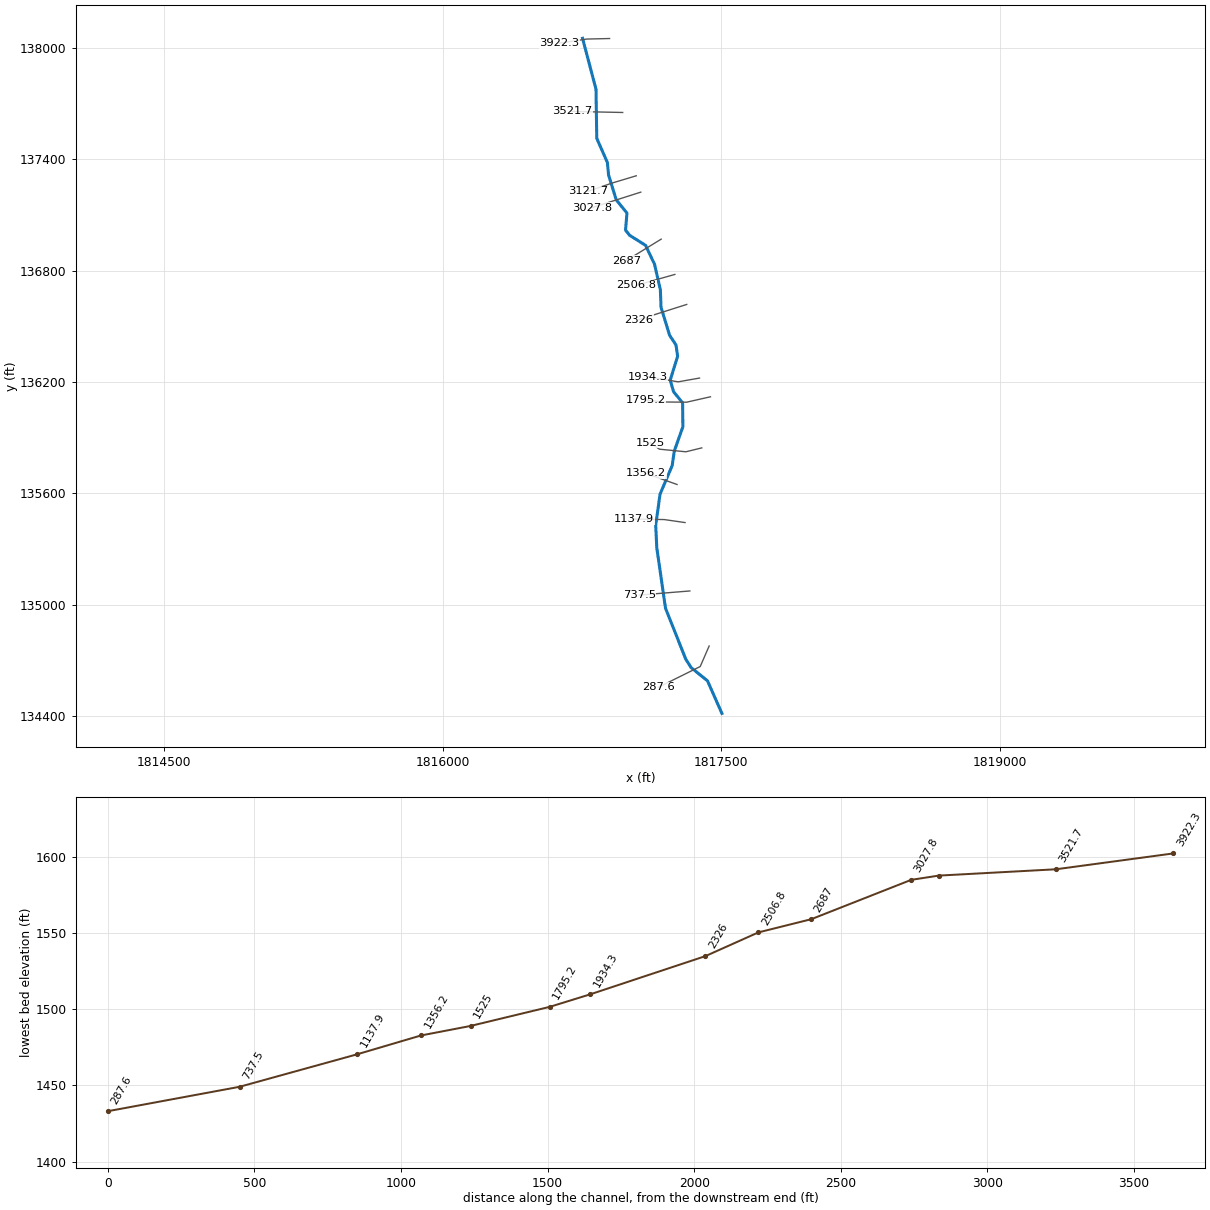
--- Turnhole Branch.prj (project) ---

Proj Title=Turnhole Branch
Current Plan=p01
Default Exp/Contr=0,0
English Units
Geom File=g01
Flow File=f01
Plan File=p01
BEGIN DESCRIPTION:
END DESCRIPTION:
DSS Export Rating Curves= 0
DSS Export Rating Curve Sorted= 0
DSS Export Volume Flow Curves= 0
DXF OffsetX= 0
DXF OffsetY= 0
DXF ScaleX= 0
DXF ScaleY= 0

--- Turnhole Branch.p01 (plan) ---

Plan Title=Floodplain
Program Version=4.00
Geom File=g01
Flow File=f01
K Sum by GR=0
Std Step Tol=0.01
Critical Tol=0.01
Num of Std Step Trials=20
Max Error Tol=0.3
Flow Tol Ratio=0.001
Split Flow NTrial=30
Split Flow Tol=0.02
Split Flow Ratio=0.02
Log Output Level=0
Friction Slope Method=1
Unsteady Friction Slope Method=2
Unsteady Bridges Friction Slope Method=1
Global Log Level=0
CheckData=False
Run HTab=0
Run UNet=0
Run PostProcess=0
UNET Theta=0
UNET Theta Warmup=0
UNET ZTol=0
UNET ZSATol=0
UNET MxIter=0
UNET MaxInSteps=0
UNET DtIC=0
UNET DtMin=0
UNET MaxCRTS=0
UNET WFStab=0
UNET SFStab=0
UNET WFX=0
UNET SFX=0
UNET DSS MLevel=0
UNET DZMax Abort=0
UNET Convert EG Bridges=0
UNET Use Existing IB Tables=0
UNET Froude Limit=0
UNET Froude Power=0
Write IC File=0
Echo Input=False
Echo Output=False
Write Detailed=0

--- Turnhole Branch.f01 (steady flow) ---

Flow Title=NFF Regression Equation
Program Version=4.00
Number of Profiles=1
Profile Names=P100yr
River Rch & RM=Turnhole Branch,Main      ,3922.3
564.5587
River Rch & RM=Turnhole Branch,Main      ,2687
613.2030
River Rch & RM=Turnhole Branch,Main      ,1795.2
672.8173
River Rch & RM=Turnhole Branch,Main      ,287.6
708.4447
Boundary for River Rch & Prof#=Turnhole Branch,Main      ,1
Up Type=0
Dn Type=3
Dn Slope=0.000001

--- Turnhole Branch.g01 (geometry) ---

Geom Title=Geometry
Program Version=4.00

River Reach=Turnhole Branch ,Main
Reach XY= 30
     1816752.885       138053.12      1816825.19      137779.031
     1816829.382      137513.858     1816886.505      137383.367
     1816892.794      137316.287     1816934.194      137182.129
     1816991.841      137110.857     1816984.159      137019.091
     1817006.011      136991.121     1817091.936      136936.869
     1817140.149      136835.202     1817171.593      136697.375
     1817175.261       136602.52     1817221.378      136451.591
     1817255.798      136399.455     1817264.522      136339.116
     1817224.591      136209.776      1817242.82      136147.276
     1817291.254      136087.784      1817292.65      135958.452
     1817246.293      135826.963     1817235.036      135748.959
     1817169.904      135595.192     1817146.466       135426.79
     1817152.389      135305.381     1817199.337      134979.695
     1817307.925      134706.303     1817336.571      134660.297
     1817425.237      134588.564     1817502.629      134413.093

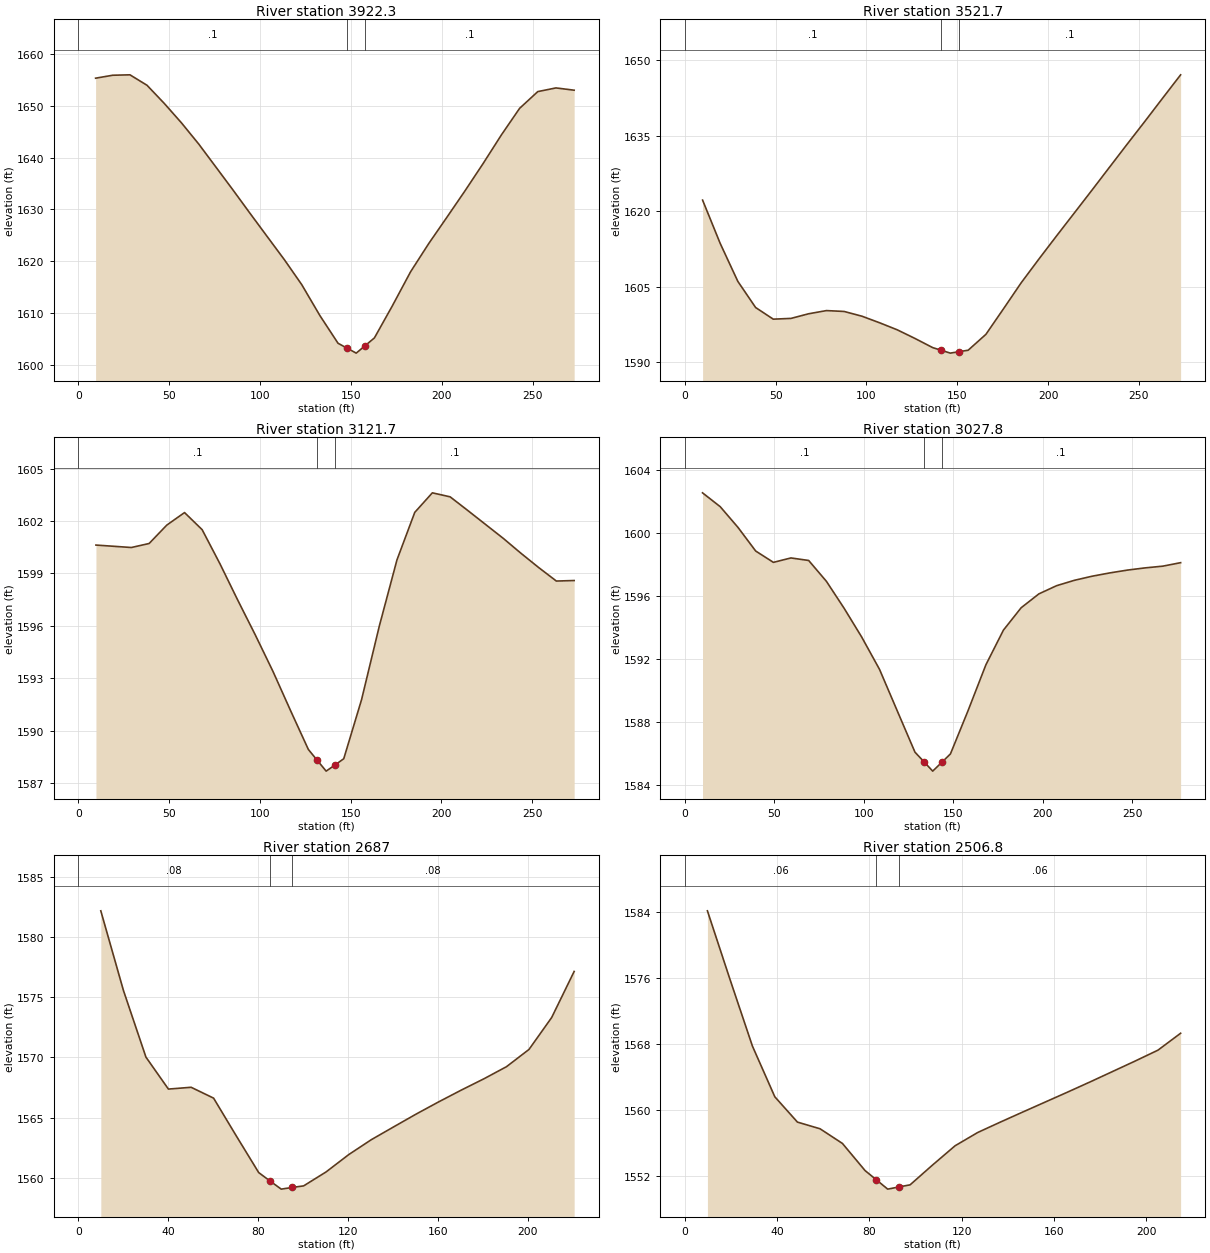
Type RM Length L Ch R = 1 ,3922.3  ,404.2,400.6,397.2
XS GIS Cut Line= 3
      1816898.34      138052.143     1816775.507      138049.226
     1816627.216      138027.041
#Sta/Elev= 30
     9.5 1655.36    18.9 1655.93    28.4 1656.01    37.8 1653.99    47.3 1650.48
    56.7 1646.75    66.2 1642.66    75.6 1638.24    85.1 1633.76    94.5 1629.24
     104 1624.73   113.4 1620.28   122.9 1615.49   132.9 1609.51   142.9 1604.15
   147.9  1603.2   152.9 1602.25   157.9 1603.72   162.9 1605.19   172.8  1611.4
   182.8 1617.96   192.8 1623.42   202.8  1628.5   212.8 1633.63   222.8 1638.92
   232.8 1644.42   242.8 1649.54   252.8 1652.77   262.8 1653.48   272.8 1653.04
#Mann= 3 , 0 , 0
       0      .1       0   147.9    .045       0   157.9      .1       0
Bank Sta=147.9,157.9
XS Rating Curve= 0 ,0
Exp/Cntr=0.3,0.1

Type RM Length L Ch R = 1 ,3521.7  ,393.6,400,407.2
XS GIS Cut Line= 3
      1816968.85      137653.321      1816832.38      137656.164
      1816695.91      137659.008
#Sta/Elev= 30
     9.8  1622.2    19.5  1613.6    29.2 1606.08      39 1600.89    48.7 1598.58
    58.5 1598.73    68.2 1599.65      78 1600.28    87.7 1600.11    97.5 1599.17
   107.2 1597.87     117 1596.46   126.7 1594.76   136.5 1592.93   141.2 1592.41
   146.2 1591.84   151.2 1592.14     156 1592.41   165.8 1595.57   175.5 1600.65
   185.2 1605.79     195 1610.52   204.7  1615.1   214.5 1619.66   224.3 1624.23
     234  1628.8   243.7 1633.36   253.5 1637.91   263.2 1642.48     273 1647.06
#Mann= 3 , 0 , 0
       0      .1       0   141.2    .045       0   151.2      .1       0
Bank Sta=141.2,151.2
XS Rating Curve= 0 ,0
Exp/Cntr=0.3,0.1

Type RM Length L Ch R = 1 ,3121.7  ,93.6,93.8,93.4
XS GIS Cut Line= 3
     1817041.919      137312.016     1816911.278      137272.521
     1816782.061      137228.179
#Sta/Elev= 30
     9.7 1600.62    19.5 1600.55    29.2 1600.48      39 1600.71    48.7 1601.76
    58.5 1602.48    68.2  1601.5      78 1599.55    87.7 1597.49    97.5 1595.47
   107.2 1593.39     117 1591.12   126.7 1588.92   131.5 1588.31   136.5 1587.68
   141.5 1588.04   146.2 1588.39     156 1591.77   165.8 1595.99   175.5 1599.77
   185.3 1602.49     195 1603.61   204.8 1603.38   214.5  1602.6   224.3  1601.8
   234.1    1601   243.8 1600.15   253.6 1599.33   263.3 1598.56   273.1 1598.59
#Mann= 3 , 0 , 0
       0      .1       0   131.5    .045       0   141.5      .1       0
Bank Sta=131.5,141.5
XS Rating Curve= 0 ,0
Exp/Cntr=0.3,0.1

Type RM Length L Ch R = 1 ,3027.8  ,336.4,340.8,345.2
XS GIS Cut Line= 2
     1817066.253      137223.696     1816802.363      137139.625
#Sta/Elev= 30
     9.9 1602.54    19.8 1601.66    29.7 1600.35    39.6 1598.85    49.5 1598.13
    59.3 1598.41    69.2 1598.25    79.1 1596.93      89 1595.22    98.9 1593.38
   108.8 1591.34   118.7 1588.71   128.6 1586.09   133.5  1585.5   138.5 1584.89
   143.5 1585.44   148.4 1585.98   158.3 1588.74   168.2 1591.63     178 1593.83
   187.9 1595.25   197.8 1596.13   207.7 1596.65   217.6 1596.99   227.5 1597.25
   237.4 1597.46   247.3 1597.64   257.2 1597.78   267.1 1597.89     277 1598.11
#Mann= 3 , 0 , 0
       0      .1       0   133.5    .045       0   143.5      .1       0
Bank Sta=133.5,143.5
XS Rating Curve= 0 ,0
Exp/Cntr=0.3,0.1

Type RM Length L Ch R = 1 ,2687    ,186.1,180.2,174.4
XS GIS Cut Line= 2
     1817176.012      136970.316      1816988.02      136854.718
#Sta/Elev= 24
      10 1582.16    20.1 1575.54    30.1 1570.02    40.1 1567.37    50.2 1567.52
    60.2 1566.62    70.2 1563.52    80.3 1560.44    85.3 1559.75    90.3 1559.07
    95.3 1559.21   100.3 1559.34   110.3  1560.5   120.4 1561.94   130.4 1563.17
   140.4 1564.24   150.5 1565.31   160.5 1566.32   170.5 1567.29   180.6 1568.23
   190.6 1569.23   200.6 1570.66   210.7 1573.31   220.7 1577.13
#Mann= 3 , 0 , 0
       0     .08       0    85.3    .045       0    95.3     .08       0
Bank Sta=85.3,95.3
XS Rating Curve= 0 ,0
Exp/Cntr=0.3,0.1

Type RM Length L Ch R = 1 ,2506.8  ,180.1,180.7,181.4
XS GIS Cut Line= 2
     1817249.574      136779.989       1817042.9      136721.606
#Sta/Elev= 24
     9.8 1584.17    19.5 1575.92    29.3 1567.76      39 1561.61    48.8 1558.54
    58.6 1557.73    68.3 1555.95    78.1 1552.66    82.9 1551.56    87.9 1550.41
    92.9 1550.68    97.6 1550.93   107.4 1553.35   117.1 1555.67   126.9 1557.28
   136.7 1558.54   146.4 1559.76   156.2 1560.98     166  1562.2   175.7 1563.43
   185.5  1564.7   195.2 1565.96     205 1567.27   214.8 1569.32
#Mann= 3 , 0 , 0
       0     .06       0    82.9    .045       0    92.9     .06       0
Bank Sta=82.9,92.9
XS Rating Curve= 0 ,0
Exp/Cntr=0.3,0.1

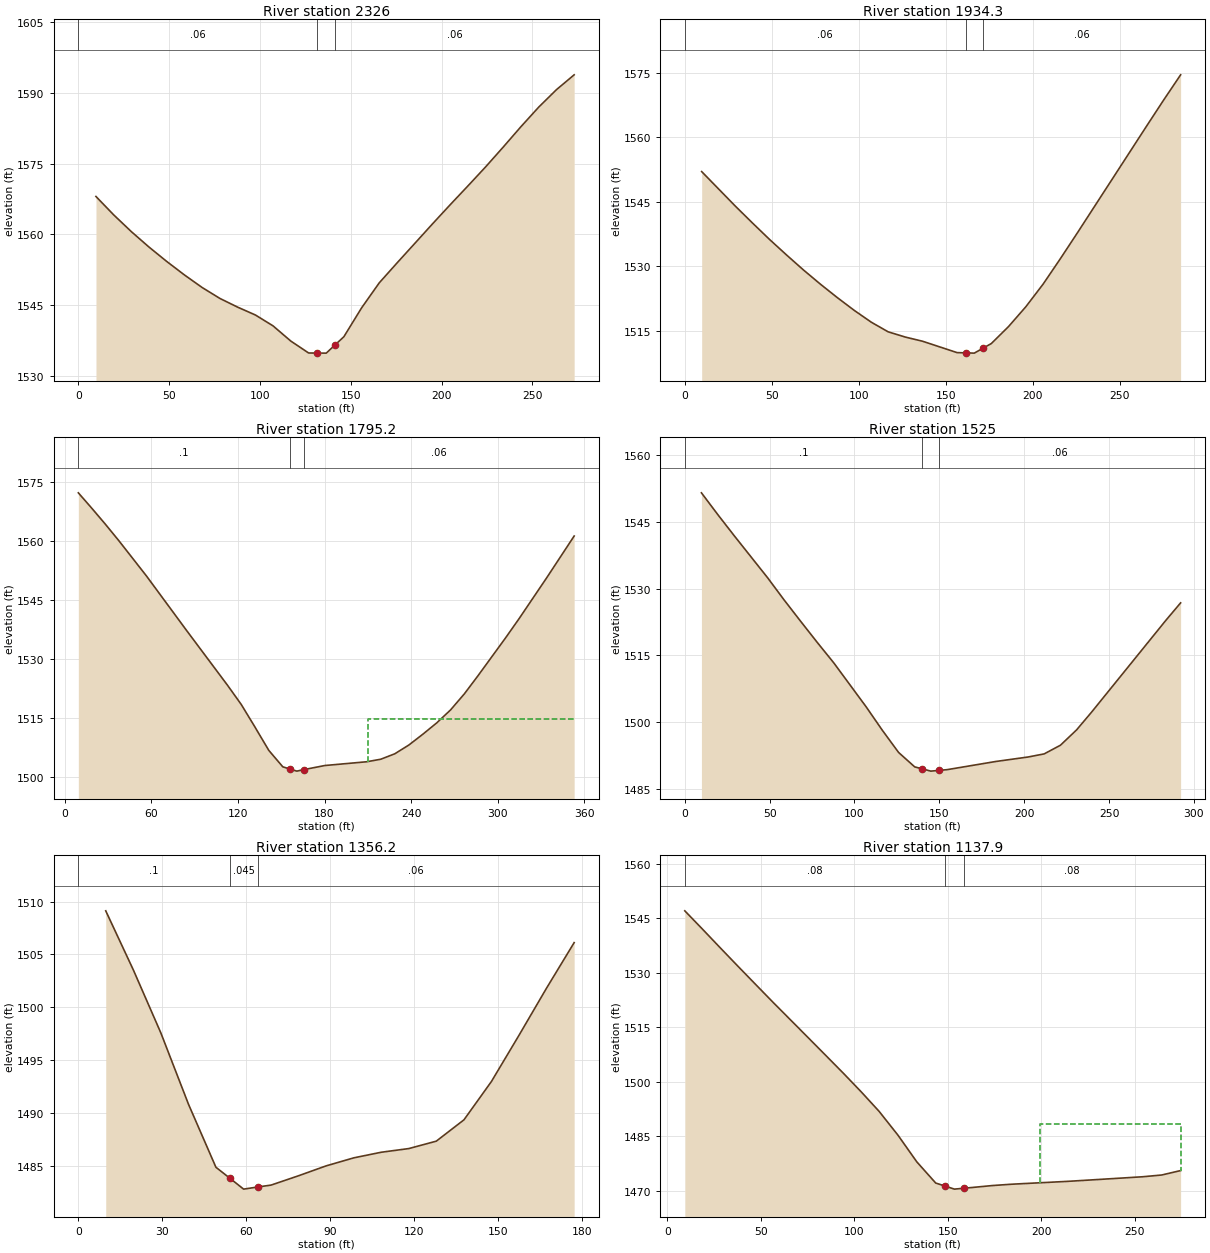
Type RM Length L Ch R = 1 ,2326    ,401.5,391.8,382.1
XS GIS Cut Line= 3
     1817313.514      136618.202      1817183.44      136576.815
     1817053.366      136535.427
#Sta/Elev= 30
     9.7 1568.05    19.5 1564.14    29.3 1560.56      39  1557.3    48.8 1554.24
    58.5  1551.4    68.2 1548.75      78 1546.43    87.8 1544.58    97.5 1542.93
   107.2 1540.63     117  1537.4   126.8 1534.88   131.5 1534.86   136.5 1534.85
   141.5 1536.64   146.2 1538.32     156 1544.46   165.7 1549.75   175.5 1553.97
   185.3 1558.12     195 1562.24   204.7 1566.28   214.5 1570.28   224.3 1574.34
     234 1578.54   243.7 1582.84   253.5 1586.99   263.3  1590.7     273 1593.83
#Mann= 3 , 0 , 0
       0     .06       0   131.5    .045       0   141.5     .06       0
Bank Sta=131.5,141.5
XS Rating Curve= 0 ,0
Exp/Cntr=0.3,0.1

Type RM Length L Ch R = 1 ,1934.3  ,136,139,141.9
XS GIS Cut Line= 3
      1817382.23      136221.219     1817267.089      136200.834
     1817101.529      136229.502
#Sta/Elev= 26
     9.7 1552.05    29.2 1543.96      39 1540.06    48.7 1536.28    58.5 1532.66
    68.2 1529.18      78 1525.86    87.7 1522.74    97.4 1519.78   107.2 1517.03
   116.9 1514.79   126.8 1513.57   136.7  1512.6   156.5 1509.96   161.4  1509.9
   166.4 1509.84   171.4 1510.98   176.2 1512.07   186.1 1516.02     196 1520.61
   205.9 1525.85   215.8 1531.75   225.7 1537.83   265.2 1562.48   275.1  1568.6
     285 1574.55
#Mann= 3 , 0 , 0
       0     .06       0   161.4    .045       0   171.4     .06       0
Bank Sta=161.4,171.4
XS Rating Curve= 0 ,0
Exp/Cntr=0.3,0.1

Type RM Length L Ch R = 1 ,1795.2  ,271.5,270.2,269.1
XS GIS Cut Line= 4
     1817441.069      136120.266     1817312.627      136091.074
     1817186.521      136092.242     1817091.941      136102.751
#Sta/Elev= 28
     9.4 1572.17    18.8 1568.23    28.2 1564.18    37.6 1559.97    56.5 1551.13
    84.7 1537.11   112.9 1523.29   122.3 1518.47   131.7 1512.81   141.4 1506.82
   151.1 1502.65   155.8 1502.12   160.8 1501.56   165.8 1501.95   180.2 1502.98
   209.3 1503.94     219 1504.58   228.7 1505.96   238.4 1508.17   248.1 1510.91
   257.8 1513.81   267.3 1517.07   276.9 1521.16   286.4 1525.78   305.4 1535.33
   314.9 1540.28     334 1550.63     353 1561.21
#Mann= 3 , 0 , 0
     9.4      .1       0   155.8    .045       0   165.8     .06       0
#XS Ineff= 2 , 0
                          210.07         1514.76
Permanent Ineff=
       F       F
Bank Sta=155.8,165.8
XS Rating Curve= 0 ,0
Exp/Cntr=0.3,0.1

Type RM Length L Ch R = 1 ,1525    ,173.8,168.8,163.8
XS GIS Cut Line= 4
     1817394.363        135844.7     1817309.124      135823.682
     1817166.671      135837.694     1817116.462      135872.723
#Sta/Elev= 24
     9.8  1551.5    19.5 1546.59    29.3 1541.79    48.8 1532.44    58.5 1527.47
    68.3 1522.65      78 1517.95    87.8 1513.33   106.9 1503.45   116.4 1498.21
     126 1493.22   135.5 1489.98     140 1489.53     145 1489.03     150  1489.2
   154.6 1489.36   183.2 1491.19   202.3  1492.2   211.8  1492.9   221.4 1494.85
   230.9 1498.29   239.7 1502.26   283.4 1522.83   292.2  1526.8
#Mann= 3 , 0 , 0
       0      .1       0     140    .045       0     150     .06       0
Bank Sta=140,150
XS Rating Curve= 0 ,0
Exp/Cntr=0.3,0.1

Type RM Length L Ch R = 1 ,1356.2  ,211.7,218.3,224.9
XS GIS Cut Line= 2
      1817261.25      135647.367     1817094.276      135706.917
#Sta/Elev= 20
     9.8 1509.13    19.7 1503.52    29.5 1497.58    39.4 1490.82    49.2 1484.86
    54.1 1483.84    59.1 1482.79    64.1 1482.99    68.9 1483.17    78.8 1484.06
    88.6 1484.99    98.5 1485.75   108.3 1486.28   118.2 1486.63     128 1487.33
   137.9 1489.35   147.7 1492.97   157.6 1497.36   167.4  1501.8   177.3 1506.12
#Mann= 3 , 0 , 0
       0      .1       0    54.1    .045       0    64.1     .06       0
Bank Sta=54.1,64.1
XS Rating Curve= 0 ,0
Exp/Cntr=0.3,0.1

Type RM Length L Ch R = 1 ,1137.9  ,398.5,400.4,402.3
XS GIS Cut Line= 3
     1817304.431      135441.987     1817192.359      135458.207
     1817031.223      135460.542
#Sta/Elev= 30
     9.4 1547.04    18.9 1541.97    28.3 1536.88    37.7 1531.84    47.2  1526.8
    56.6 1521.83    66.1 1516.91    75.5 1512.03    84.9 1507.14    94.4 1502.18
   103.8 1497.13   113.2 1491.85   123.3 1485.28   133.4 1477.91   143.5 1472.08
   148.5 1471.24   153.5  1470.4   158.5 1470.64   163.6 1470.88   173.7 1471.38
   183.7 1471.74   193.8 1472.01   203.9 1472.27     214 1472.54     224 1472.85
   234.1 1473.17   244.2 1473.49   254.2 1473.81   264.3 1474.29   274.4 1475.51
#Mann= 3 , 0 , 0
     9.4     .08       0   148.5    .045       0   158.5     .08       0
#XS Ineff= 2 , 0
                          199.33         1488.41
Permanent Ineff=
       F       F
Bank Sta=148.5,158.5
XS Rating Curve= 0 ,0
Exp/Cntr=0.3,0.1

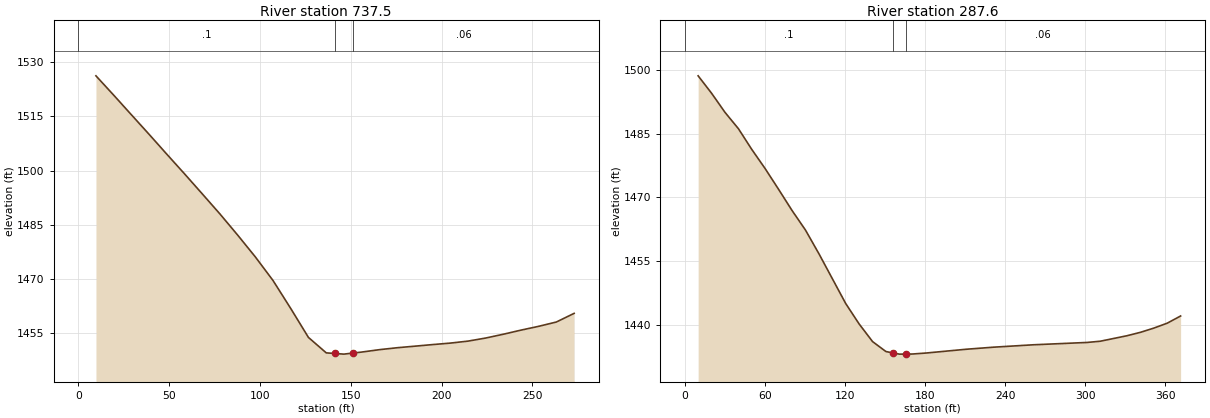
Type RM Length L Ch R = 1 ,737.5   ,442.7,449.9,457.2
XS GIS Cut Line= 3
      1817330.19      135073.174     1817194.139      135062.114
     1817058.088      135051.053
#Sta/Elev= 30
     9.7 1526.24    19.5 1520.87    29.2 1515.46      39 1510.01    48.7 1504.53
    58.5 1499.06    68.2 1493.55      78 1487.94    87.7 1482.12    97.5 1476.03
   107.2 1469.51     117 1461.72   126.7 1453.74   136.5 1449.46   141.2 1449.29
   146.2 1449.11   151.2 1449.41     156 1449.68   165.7 1450.34   175.5 1450.88
   185.2 1451.31     195 1451.75   204.7 1452.16   214.5 1452.71   224.2 1453.56
     234 1454.62   243.7 1455.76   253.5 1456.82   263.2 1458.01     273 1460.41
#Mann= 3 , 0 , 0
       0      .1       0   141.2    .045       0   151.2     .06       0
Bank Sta=141.2,151.2
XS Rating Curve= 0 ,0
Exp/Cntr=0.3,0.1

Type RM Length L Ch R = 1 ,287.6   ,287,287.6,288.1
XS GIS Cut Line= 3
     1817434.063      134776.299     1817386.037      134665.693
     1817161.315       134554.03
#Sta/Elev= 29
      10 1498.66    20.1 1494.54    30.1 1490.06    40.2 1486.19    50.2 1481.31
    60.3 1476.75    70.3  1471.9    80.4  1466.9    90.4 1462.32   100.5 1456.73
   120.6 1444.98   130.6 1440.19   140.7 1436.02   150.7 1433.68   155.7 1433.37
   160.7 1433.07   165.7 1433.08   170.8  1433.1   180.8 1433.33   210.9 1434.22
     231  1434.7   261.1 1435.27   301.3 1435.82   311.3 1436.11   331.4 1437.41
   341.4 1438.21   351.4  1439.2   361.5 1440.37   371.5 1442.06
#Mann= 3 , 0 , 0
       0      .1       0   155.7    .045       0   165.7     .06       0
Bank Sta=155.7,165.7
XS Rating Curve= 0 ,0
Exp/Cntr=0.3,0.1

Chan Stop Cuts=-1
Use User Specified Reach Order=0